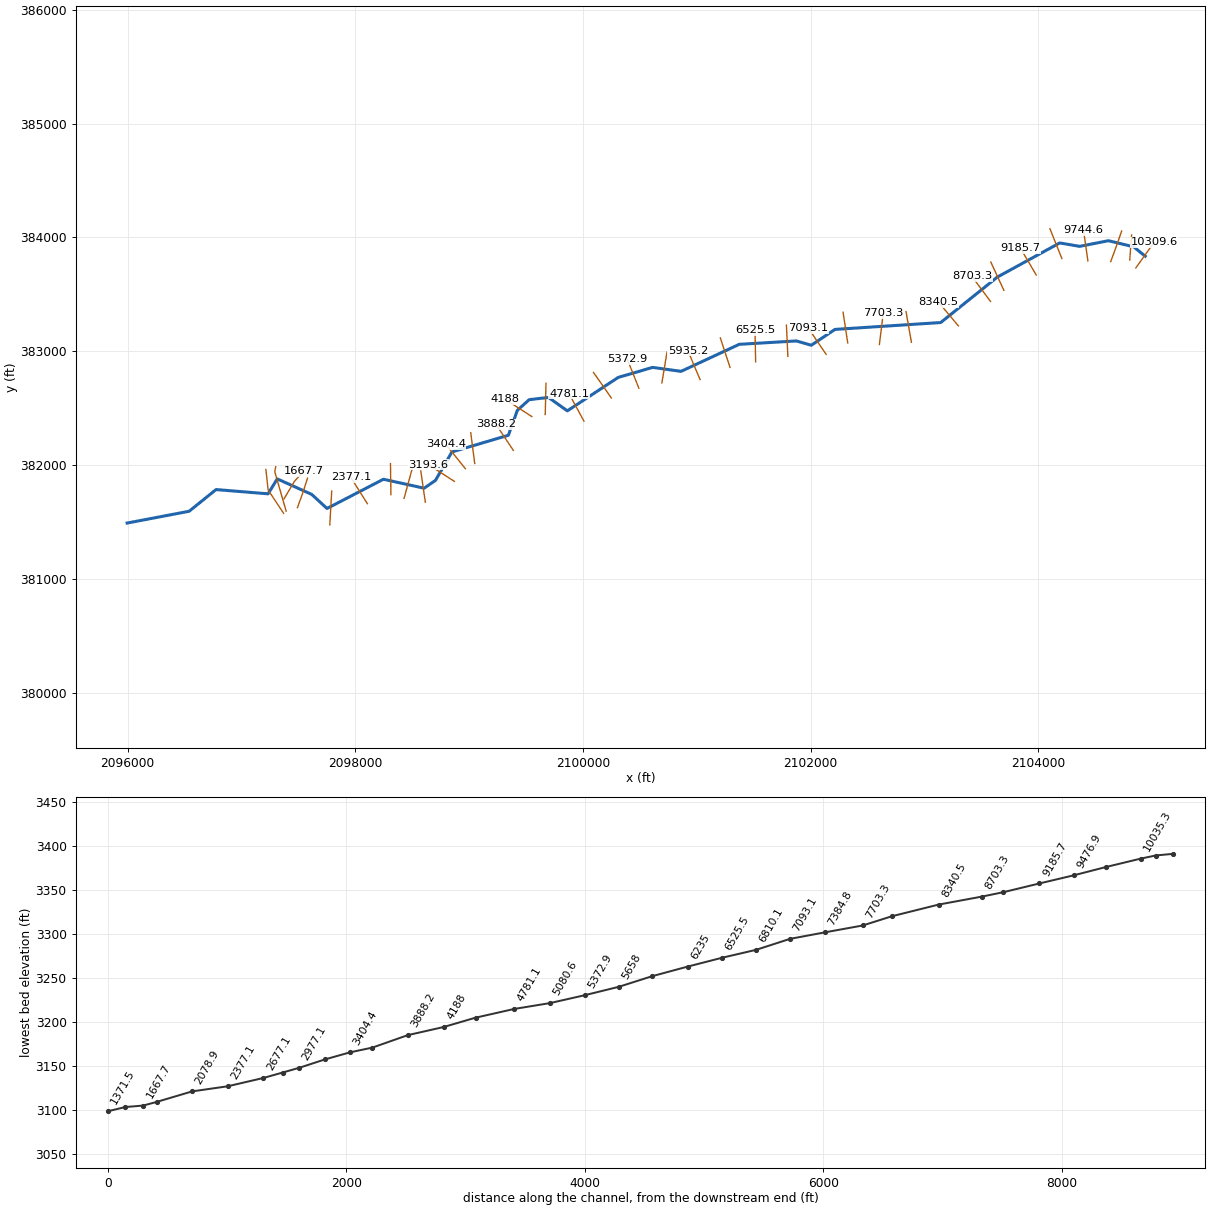
--- OldFieldBr.prj (project) ---

Proj Title=OldFieldBr
Current Plan=p01
Default Exp/Contr=0,0
English Units
Geom File=g01
Flow File=f01
Plan File=p01
BEGIN DESCRIPTION:
END DESCRIPTION:
DSS Export Rating Curves= 0
DSS Export Rating Curve Sorted= 0
DSS Export Volume Flow Curves= 0
DXF OffsetX= 0
DXF OffsetY= 0
DXF ScaleX= 0
DXF ScaleY= 0

--- OldFieldBr.p01 (plan) ---

Plan Title=Floodplain
Program Version=4.00
Geom File=g01
Flow File=f01
K Sum by GR=0
Std Step Tol=0.01
Critical Tol=0.01
Num of Std Step Trials=20
Max Error Tol=0.3
Flow Tol Ratio=0.001
Split Flow NTrial=30
Split Flow Tol=0.02
Split Flow Ratio=0.02
Log Output Level=0
Friction Slope Method=1
Unsteady Friction Slope Method=2
Unsteady Bridges Friction Slope Method=1
Global Log Level=0
CheckData=False
Run HTab=0
Run UNet=0
Run PostProcess=0
UNET Theta=0
UNET Theta Warmup=0
UNET ZTol=0
UNET ZSATol=0
UNET MxIter=0
UNET MaxInSteps=0
UNET DtIC=0
UNET DtMin=0
UNET MaxCRTS=0
UNET WFStab=0
UNET SFStab=0
UNET WFX=0
UNET SFX=0
UNET DSS MLevel=0
UNET DZMax Abort=0
UNET Convert EG Bridges=0
UNET Use Existing IB Tables=0
UNET Froude Limit=0
UNET Froude Power=0
Write IC File=0
Echo Input=False
Echo Output=False
Write Detailed=0

--- OldFieldBr.f01 (steady flow) ---

Flow Title=NFF Regression Equation
Program Version=4.00
Number of Profiles=1
Profile Names=P100yr
River Rch & RM=OldFieldBr,Main      ,10309.6
519.1744
River Rch & RM=OldFieldBr,Main      ,8340.5
545.8678
River Rch & RM=OldFieldBr,Main      ,7948
628.0419
River Rch & RM=OldFieldBr,Main      ,7384.8
690.3383
River Rch & RM=OldFieldBr,Main      ,5658
751.2578
River Rch & RM=OldFieldBr,Main      ,2677.1
822.0363
River Rch & RM=OldFieldBr,Main      ,238.8
898.5345
Boundary for River Rch & Prof#=OldFieldBr,Main      ,1
Up Type=0
Dn Type=3
Dn Slope=0.027454

--- OldFieldBr.g01 (geometry) ---

Geom Title=USGS 10m DEM
Program Version=4.00

River Reach=OldFieldBr      ,Main
Reach XY= 30
     2104940.087      383835.569     2104838.849       383918.08
     2104617.051      383971.751     2104364.461       383922.17
      2104188.61      383951.819     2103640.609      383652.259
     2103143.728      383253.527     2102214.377      383193.206
     2102006.832      383054.161     2101876.988       383091.99
     2101373.973      383062.341     2100862.778      382825.146
     2100613.315      382859.908     2100310.532      382771.805
     2099863.904      382478.556     2099698.277      382596.131
      2099528.56      382576.706     2099424.277      382482.646
     2099345.803      382264.404     2098849.694      382117.653
     2098705.537       381868.19     2098605.343       381799.69
     2098248.178      381878.352      2097752.67      381621.794
     2097617.715      381745.503     2097315.088      381881.481
     2097235.303      381750.305     2096777.846      381787.689
     2096541.139      381597.257     2095996.693      381493.823

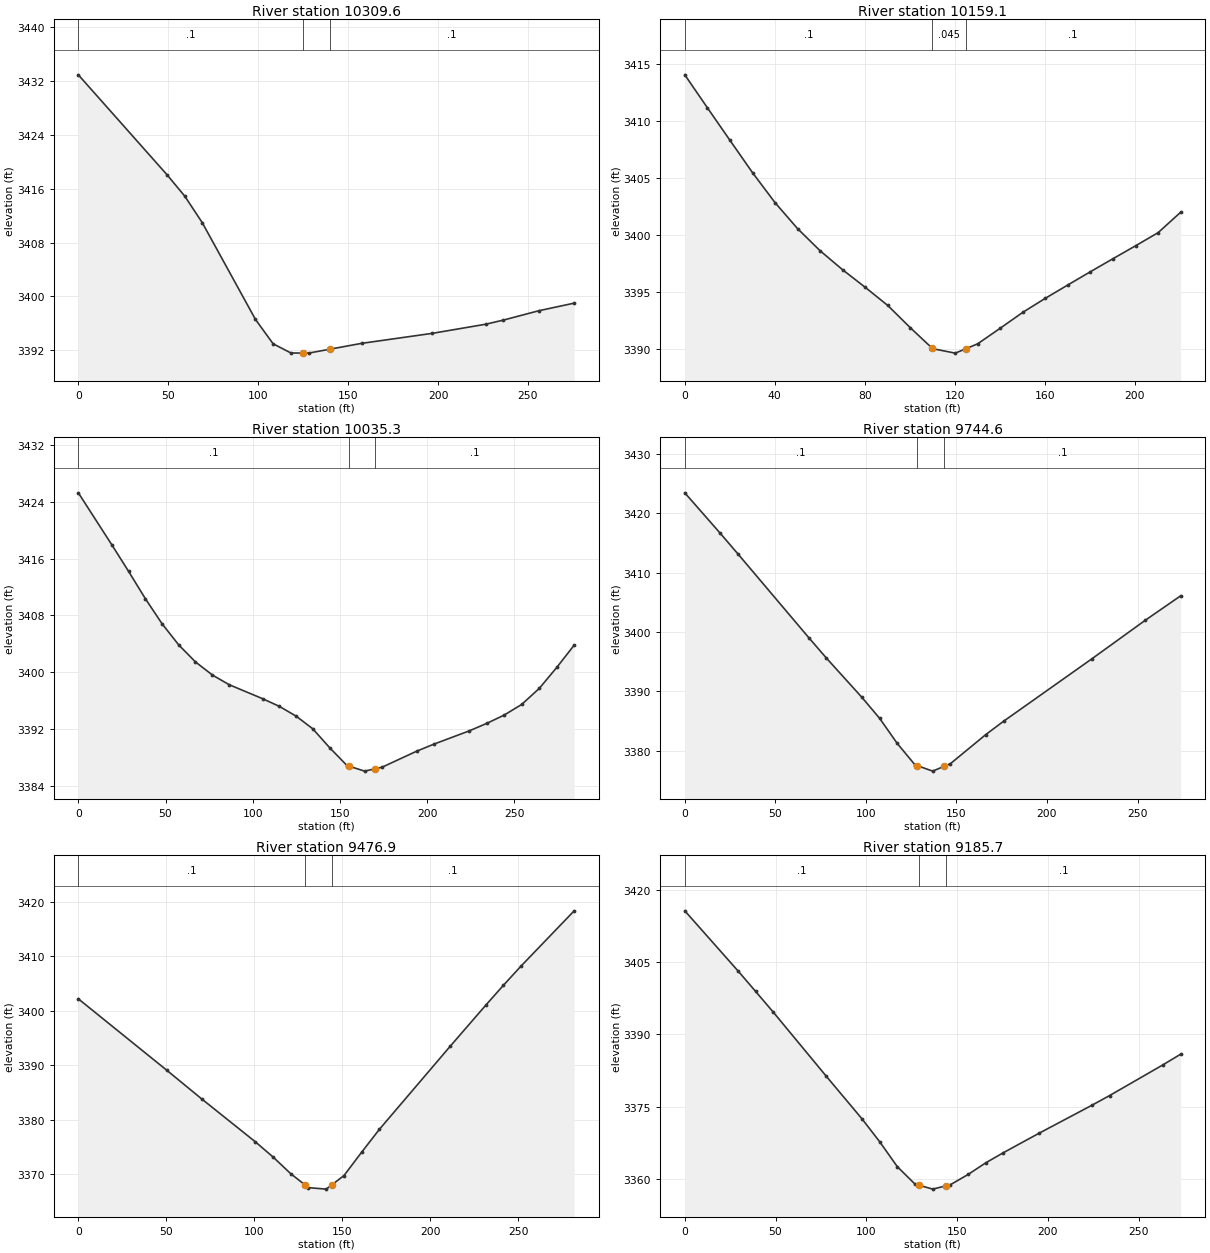
Type RM Length L Ch R = 1 ,10309.6 ,137.8,150.5,163.1
XS GIS Cut Line= 2
     2104857.713      383733.142     2105017.888      383957.535
#Sta/Elev= 16
       0 3432.89    49.2 3418.09    59.1 3414.91    68.9 3410.95    98.5 3396.58
   108.3 3392.97   118.2  3391.6   124.8 3391.59     128 3391.58   139.8 3392.16
   157.5 3393.03   196.9 3394.52   226.5 3395.87   236.3 3396.48     256 3397.87
   275.7    3399
#Mann= 3 , 0 , 0
       0      .1       0   124.8    .045       0   139.8      .1       0
Bank Sta=124.8,139.8
XS Rating Curve= 0 ,0
Exp/Cntr=0.3,0.1

Type RM Length L Ch R = 1 ,10159.1 ,129.8,123.8,117.9
XS GIS Cut Line= 2
     2104804.088      383801.528     2104820.446      384021.342
#Sta/Elev= 25
       0 3414.08      10  3411.2      20 3408.35    30.1 3405.49    40.1 3402.86
    50.1 3400.58    60.1 3398.64    70.1 3396.97    80.2 3395.42    90.2 3393.83
   100.2 3391.88   109.8  3390.1   110.2 3390.03   120.2 3389.64   124.8 3390.01
   130.2 3390.46   140.3 3391.84   150.3 3393.23   160.3 3394.46   170.3 3395.63
   180.3 3396.79   190.4 3397.94   200.4 3399.07   210.4 3400.22   220.4 3402.01
#Mann= 3 , 0 , 0
       0      .1       0   109.8    .045       0   124.8      .1       0
Bank Sta=109.8,124.8
XS Rating Curve= 0 ,0
Exp/Cntr=0.3,0.1

Type RM Length L Ch R = 1 ,10035.3 ,280,290.7,301.3
XS GIS Cut Line= 3
     2104637.062      383788.374     2104686.861      383923.607
     2104732.742      384056.182
#Sta/Elev= 28
       0 3425.25    19.2 3417.94    28.8 3414.21    38.4 3410.38      48 3406.84
    57.6 3403.85    67.2 3401.46    76.9 3399.62    86.5 3398.26   105.7 3396.29
   115.3 3395.21   124.9 3393.84   134.5 3392.05   144.1 3389.41   154.1 3386.89
   155.4 3386.79   164.2  3386.1   170.4 3386.44   174.2 3386.65   194.2 3388.92
   204.2 3389.92   224.3 3391.77   234.3 3392.82   244.3 3393.99   254.3 3395.48
   264.4 3397.74   274.4 3400.68   284.4 3403.82
#Mann= 3 , 0 , 0
       0      .1       0   155.4    .045       0   170.4      .1       0
Bank Sta=155.4,170.4
XS Rating Curve= 0 ,0
Exp/Cntr=0.3,0.1

Type RM Length L Ch R = 1 ,9744.6  ,262.3,267.7,273
XS GIS Cut Line= 2
     2104436.616      383794.645     2104397.859      384065.671
#Sta/Elev= 18
       0 3423.44    19.6 3416.62    29.3 3413.17    68.4 3399.08    78.2 3395.62
    97.8 3389.01   107.6 3385.47   117.3 3381.26   127.1 3377.65   128.4 3377.51
   136.9 3376.59   143.4 3377.43   146.7 3377.85   166.2 3382.74     176 3384.98
   224.9 3395.52   254.2 3401.97   273.8  3406.1
#Mann= 3 , 0 , 0
       0      .1       0   128.4    .045       0   143.4      .1       0
Bank Sta=128.4,143.4
XS Rating Curve= 0 ,0
Exp/Cntr=0.3,0.1

Type RM Length L Ch R = 1 ,9476.9  ,306.2,291.3,313.6
XS GIS Cut Line= 2
     2104207.895      383815.138     2104103.112      384076.751
#Sta/Elev= 18
       0 3402.17    50.3 3389.05    70.4 3383.72   100.6 3375.92   110.7 3373.12
   120.8 3370.04   129.1 3367.94   130.8  3367.5   140.9 3367.23   144.1 3368.02
     151 3369.73     161    3374   171.1 3378.21   211.4 3393.48   231.5 3400.98
   241.6 3404.66   251.6 3408.18   281.8 3418.33
#Mann= 3 , 0 , 0
       0      .1       0   129.1    .045       0   144.1      .1       0
Bank Sta=129.1,144.1
XS Rating Curve= 0 ,0
Exp/Cntr=0.3,0.1

Type RM Length L Ch R = 1 ,9185.7  ,305,302.5,300.3
XS GIS Cut Line= 2
     2103983.202      383670.071     2103844.337      383905.293
#Sta/Elev= 21
       0 3415.58    29.3 3403.13      39 3398.88    48.8 3394.55      78 3381.26
    97.6 3372.46   107.3 3367.74   117.1 3362.53   126.8 3358.93     129 3358.69
   136.6 3357.87     144 3358.56   146.3 3358.78   156.1 3360.91   165.8 3363.32
   175.6 3365.44   195.1 3369.44   224.4 3375.28   234.1 3377.28   263.4 3383.63
   273.2 3385.85
#Mann= 3 , 0 , 0
       0      .1       0     129    .045       0     144      .1       0
Bank Sta=129,144
XS Rating Curve= 0 ,0
Exp/Cntr=0.3,0.1

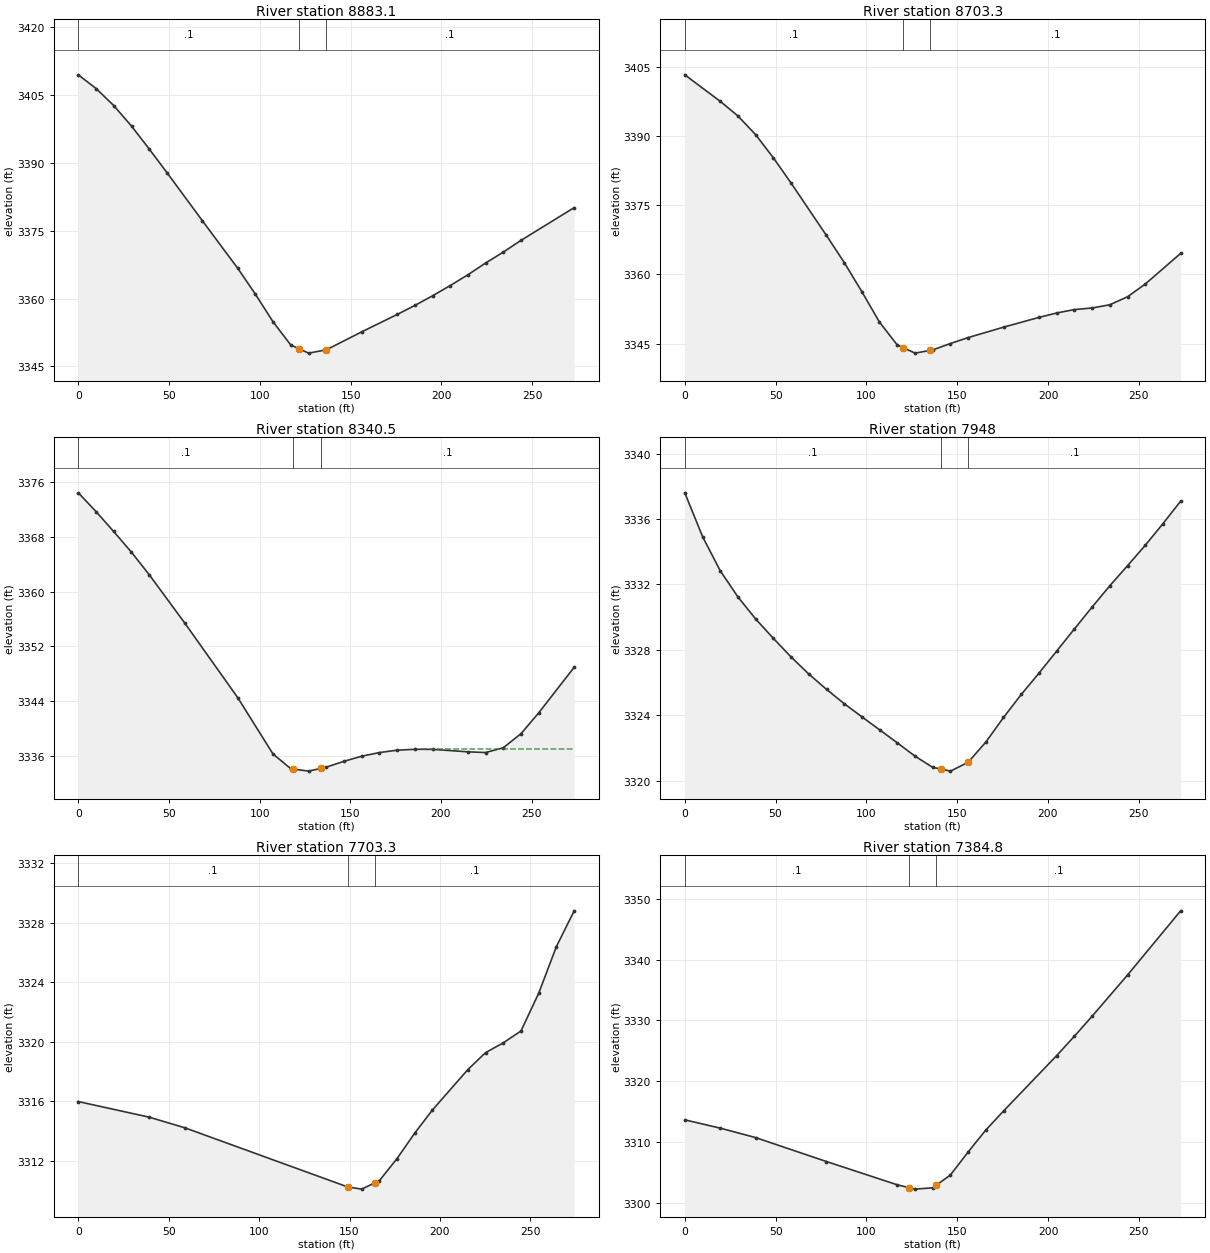
Type RM Length L Ch R = 1 ,8883.1  ,175.2,179.8,184.5
XS GIS Cut Line= 2
     2103698.299       383536.79     2103583.591      383784.609
#Sta/Elev= 24
       0 3409.38     9.8 3406.35    19.5  3402.6    29.3 3398.06      39 3393.02
    48.8  3387.8    68.3 3377.18    87.8 3366.67    97.5 3360.97   107.3 3354.83
     117 3349.74   121.6  3348.9   126.8 3347.94   136.6 3348.67     156 3352.62
   175.6 3356.47   185.3 3358.46   195.1 3360.59   204.8 3362.85   214.6 3365.24
   224.3 3367.83   234.1 3370.25   243.8 3372.83   273.1 3380.06
#Mann= 3 , 0 , 0
       0      .1       0   121.6    .045       0   136.6      .1       0
Bank Sta=121.6,136.6
XS Rating Curve= 0 ,0
Exp/Cntr=0.3,0.1

Type RM Length L Ch R = 1 ,8703.3  ,361.4,362.8,364.2
XS GIS Cut Line= 3
     2103581.144      383438.587     2103499.693      383548.123
     2103418.243      383657.659
#Sta/Elev= 26
       0  3403.3    19.5 3397.56    29.2  3394.4      39 3390.32    48.8 3385.28
    58.5 3379.83      78 3368.45    87.8 3362.58    97.5 3356.25   107.2 3349.65
     117 3344.69   120.2 3344.11   126.8 3342.93   135.2 3343.53   136.5 3343.62
   146.2 3345.01     156  3346.3   175.5 3348.56     195 3350.68   204.8 3351.64
   214.5 3352.38   224.2 3352.72     234 3353.42   243.8 3355.16   253.5 3357.91
     273 3364.56
#Mann= 3 , 0 , 0
       0      .1       0   120.2    .045       0   135.2      .1       0
Bank Sta=120.2,135.2
XS Rating Curve= 0 ,0
Exp/Cntr=0.3,0.1

Type RM Length L Ch R = 1 ,8340.5  ,405.2,392.5,379.8
XS GIS Cut Line= 2
     2103299.135      383224.107     2103122.893      383433.241
#Sta/Elev= 25
       0 3374.37     9.8 3371.63    19.5 3368.74    29.3 3365.73    39.1 3362.45
    58.6 3355.45    87.9 3344.56   107.4 3336.34   117.2  3334.2   118.6 3334.15
     127 3333.85   133.6 3334.24   136.8 3334.43   146.5 3335.28   156.3 3336.02
     166 3336.55   175.8  3336.9   185.6 3337.03   195.4 3337.02   214.9 3336.66
   224.7 3336.56   234.4 3337.25   244.2 3339.31     254 3342.35   273.5 3348.97
#Mann= 3 , 0 , 0
       0      .1       0   118.6    .045       0   133.6      .1       0
#XS Ineff= 2 , 0
                          189.19         3337.04
Permanent Ineff=
       F       F
Bank Sta=118.6,133.6
XS Rating Curve= 0 ,0
Exp/Cntr=0.3,0.1

Type RM Length L Ch R = 1 ,7948    ,251.4,244.7,238
XS GIS Cut Line= 2
     2102886.145      383080.714     2102838.946      383349.826
#Sta/Elev= 30
       0  3337.6     9.8 3334.92    19.5 3332.84    29.3 3331.23      39 3329.89
    48.8  3328.7    58.6 3327.56    68.3 3326.52    78.1 3325.58    87.8 3324.71
    97.6  3323.9   107.3 3323.11   117.1 3322.31   126.8  3321.5   136.6 3320.81
   141.1 3320.71   146.4 3320.58   156.1 3321.12   165.9 3322.36   175.6 3323.86
   185.4 3325.27   195.2 3326.58   204.9 3327.92   214.7 3329.28   224.4 3330.61
   234.2 3331.92     244 3333.15   253.7 3334.39   263.5 3335.72   273.2 3337.09
#Mann= 3 , 0 , 0
       0      .1       0   141.1    .045       0   156.1      .1       0
Bank Sta=141.1,156.1
XS Rating Curve= 0 ,0
Exp/Cntr=0.3,0.1

Type RM Length L Ch R = 1 ,7703.3  ,312.3,318.5,324.6
XS GIS Cut Line= 2
     2102605.059      383060.883     2102638.394      383333.015
#Sta/Elev= 17
       0 3315.97    39.2 3314.92    58.8 3314.21   148.9 3310.23   156.7 3310.08
   163.9  3310.5   166.5 3310.65   176.2 3312.13     186 3313.84   195.8  3315.4
   215.4 3318.12   225.2 3319.26     235 3319.92   244.8 3320.72   254.6 3323.26
   264.4  3326.4   274.2  3328.8
#Mann= 3 , 0 , 0
       0      .1       0   148.9    .045       0   163.9      .1       0
Bank Sta=148.9,163.9
XS Rating Curve= 0 ,0
Exp/Cntr=0.3,0.1

Type RM Length L Ch R = 1 ,7384.8  ,281.7,291.7,301.7
XS GIS Cut Line= 3
     2102326.914      383074.522      2102306.33      383209.461
     2102285.746        383344.4
#Sta/Elev= 18
       0 3313.64    19.5 3312.28      39 3310.72      78 3306.78     117 3302.95
   123.4 3302.48   126.8 3302.24   136.5 3302.46   138.4 3302.87   146.2 3304.55
     156 3308.35   165.8 3311.99   175.5  3315.1   204.8 3324.23   214.5  3327.4
   224.2 3330.67   243.8 3337.49     273 3348.04
#Mann= 3 , 0 , 0
       0      .1       0   123.4    .045       0   138.4      .1       0
Bank Sta=123.4,138.4
XS Rating Curve= 0 ,0
Exp/Cntr=0.3,0.1

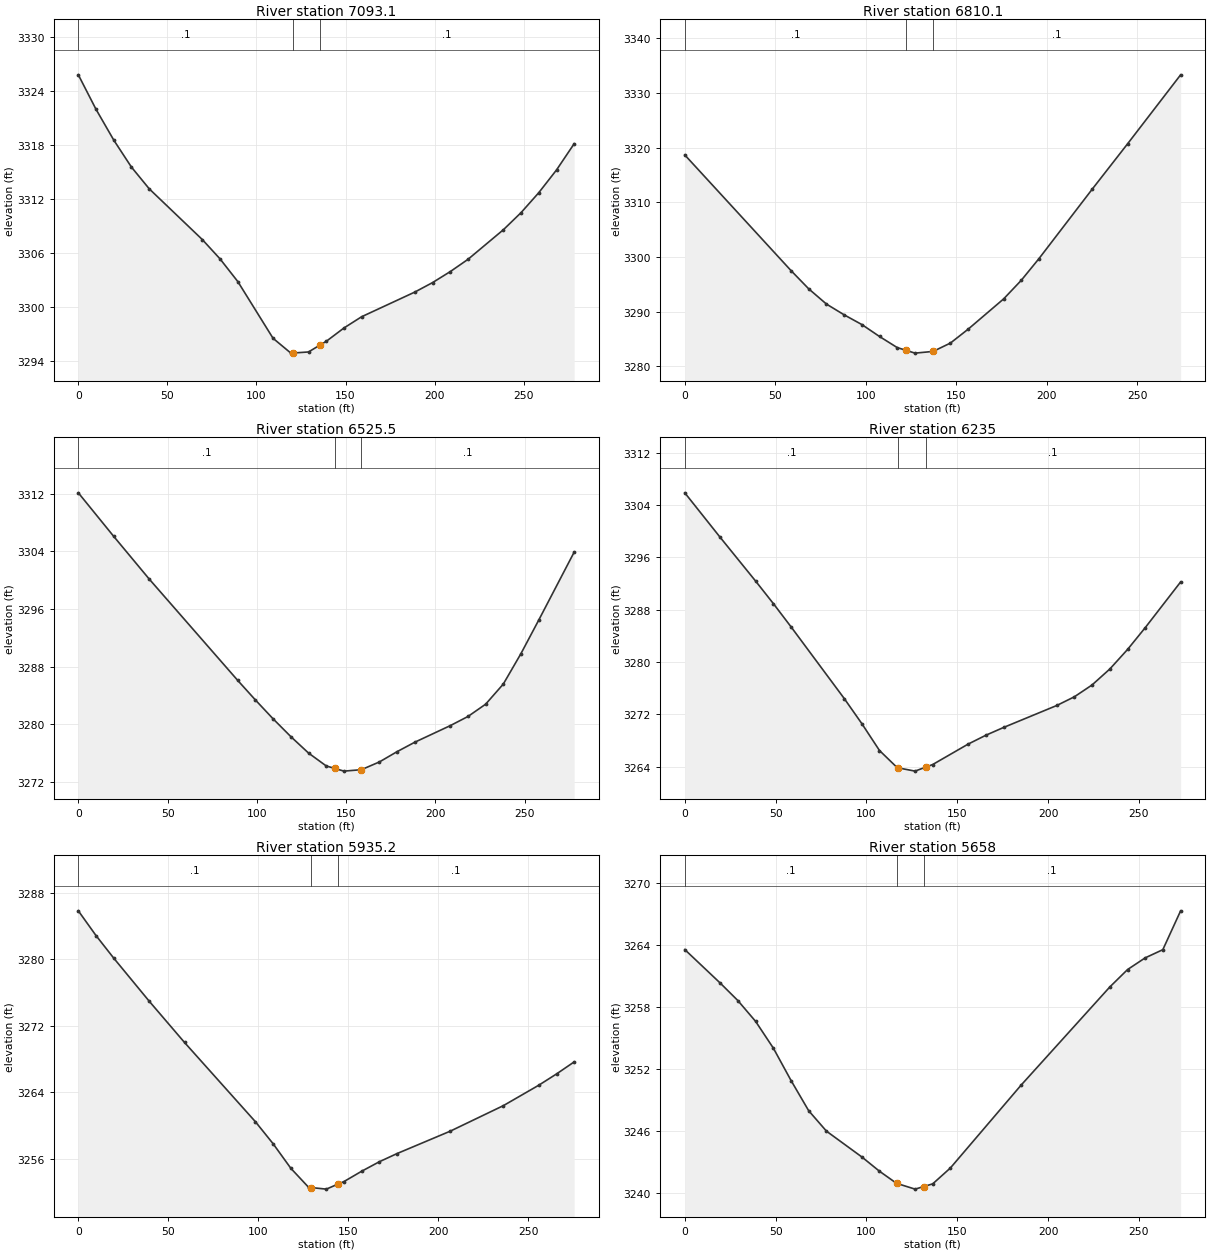
Type RM Length L Ch R = 1 ,7093.1  ,295.7,283,270.3
XS GIS Cut Line= 2
     2102137.324       382973.82     2101981.088      383204.161
#Sta/Elev= 25
       0 3325.83     9.9    3322    19.9 3318.56    29.8 3315.56    39.8 3313.14
    69.6 3307.49    79.5 3305.35    89.5 3302.82   109.3  3296.5   119.3 3294.85
   120.4 3294.86   129.2 3294.98   135.4 3295.72   139.2 3296.17   149.1 3297.65
     159  3298.9   188.9 3301.65   198.8  3302.7   208.8 3303.93   218.7 3305.29
   238.6 3308.59   248.5 3310.49   258.4  3312.7   268.4 3315.24   278.3 3318.16
#Mann= 3 , 0 , 0
       0      .1       0   120.4    .045       0   135.4      .1       0
Bank Sta=120.4,135.4
XS Rating Curve= 0 ,0
Exp/Cntr=0.3,0.1

Type RM Length L Ch R = 1 ,6810.1  ,285.1,284.6,284.1
XS GIS Cut Line= 2
     2101800.852      382956.623     2101788.321      383230.351
#Sta/Elev= 19
       0 3318.64    58.7 3297.51    68.5 3294.17    78.3 3291.39    88.1 3289.42
    97.9 3287.64   107.6 3285.47   117.4 3283.44   122.2 3282.95   127.2 3282.43
   137.2 3282.74   146.8 3284.27   156.6 3286.81   176.2 3292.34   185.9 3295.72
   195.7 3299.69   225.1 3312.37   244.7 3320.68     274 3333.28
#Mann= 3 , 0 , 0
       0      .1       0   122.2    .045       0   137.2      .1       0
Bank Sta=122.2,137.2
XS Rating Curve= 0 ,0
Exp/Cntr=0.3,0.1

Type RM Length L Ch R = 1 ,6525.5  ,283.8,290.4,297.1
XS GIS Cut Line= 2
     2101517.898      382908.403     2101512.252      383186.144
#Sta/Elev= 22
       0 3312.16    19.8 3306.11    39.7 3300.17    89.3 3286.07    99.2 3283.35
   109.1 3280.73   119.1 3278.24     129 3275.96   138.9 3274.17   143.6 3273.83
   148.8 3273.45   158.6 3273.65   168.7 3274.73   178.6 3276.16   188.5 3277.47
   208.4 3279.78   218.3 3281.05   228.2 3282.76   238.1 3285.56     248  3289.8
     258 3294.48   277.8 3303.91
#Mann= 3 , 0 , 0
       0      .1       0   143.6    .045       0   158.6      .1       0
Bank Sta=143.6,158.6
XS Rating Curve= 0 ,0
Exp/Cntr=0.3,0.1

Type RM Length L Ch R = 1 ,6235    ,297.8,299.9,301.9
XS GIS Cut Line= 2
     2101292.621      382859.692     2101207.491      383119.079
#Sta/Elev= 23
       0 3305.87    19.5 3299.06      39 3292.38    48.8 3288.93    58.5 3285.39
    87.8 3274.43    97.5 3270.59   107.2 3266.49     117 3263.86   117.6 3263.83
   126.8 3263.34   132.6 3263.95   136.5 3264.35     156 3267.47   165.8 3268.83
   175.5 3270.01   204.8 3273.37   214.5  3274.7   224.2  3276.5     234 3278.94
   243.8 3281.94   253.5 3285.26     273 3292.25
#Mann= 3 , 0 , 0
       0      .1       0   117.6    .045       0   132.6      .1       0
Bank Sta=117.6,132.6
XS Rating Curve= 0 ,0
Exp/Cntr=0.3,0.1

Type RM Length L Ch R = 1 ,5935.2  ,290,277.2,264.3
XS GIS Cut Line= 2
     2101029.654      382753.232     2100922.206      383006.936
#Sta/Elev= 21
       0 3285.84     9.8 3282.87    19.7 3280.14    39.4 3274.96      59    3270
    98.4 3260.46   108.2 3257.82   118.1 3254.85   127.9 3252.58   129.3 3252.54
   137.8 3252.35   144.3 3252.96   147.6 3253.26   157.4  3254.5   167.3 3255.65
   177.1 3256.63   206.6 3259.32   236.2  3262.4   255.8 3264.85   265.7 3266.21
   275.5 3267.66
#Mann= 3 , 0 , 0
       0      .1       0   129.3    .045       0   144.3      .1       0
Bank Sta=129.3,144.3
XS Rating Curve= 0 ,0
Exp/Cntr=0.3,0.1

Type RM Length L Ch R = 1 ,5658    ,272.8,285.1,297.4
XS GIS Cut Line= 3
     2100694.143      382723.949     2100716.584      382858.592
     2100739.024      382993.234
#Sta/Elev= 21
       0 3263.55    19.5 3260.31    29.2 3258.62      39  3256.6    48.8    3254
    58.5 3250.88    68.2 3247.96      78 3245.98    97.5 3243.48   107.2  3242.1
   116.6 3240.93   126.8 3240.37   131.6 3240.62   136.5 3240.88   146.2 3242.41
   185.2 3250.44     234 3259.93   243.8 3261.62   253.5 3262.75   263.2 3263.54
     273  3267.3
#Mann= 3 , 0 , 0
       0      .1       0   116.6    .045       0   131.6      .1       0
Bank Sta=116.6,131.6
XS Rating Curve= 0 ,0
Exp/Cntr=0.3,0.1

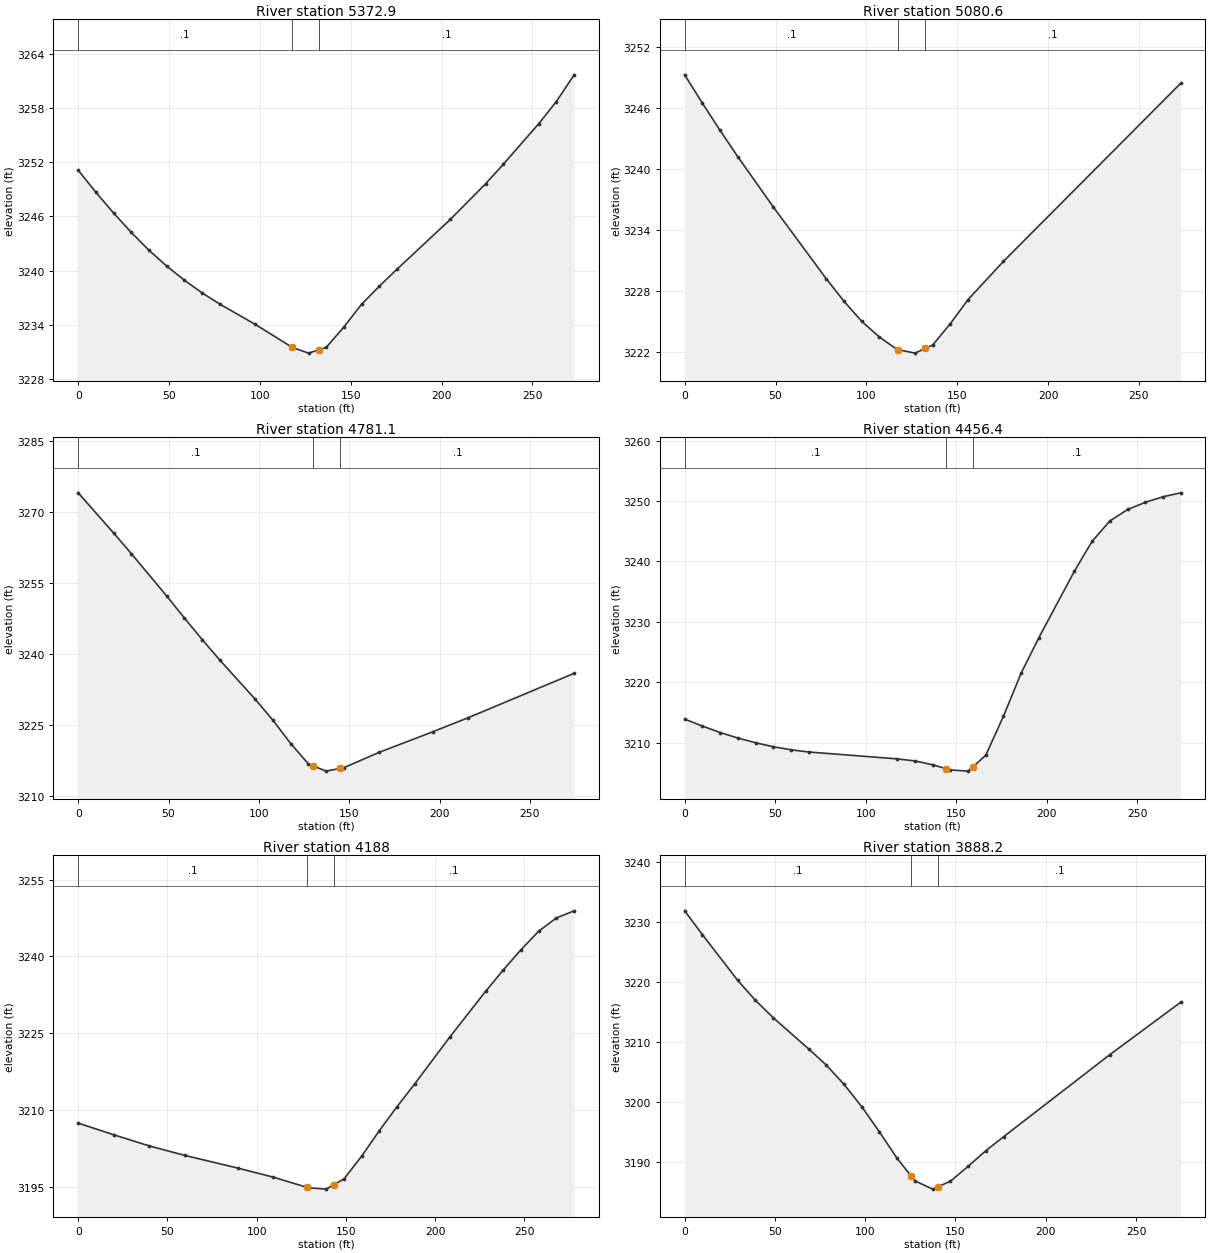
Type RM Length L Ch R = 1 ,5372.9  ,285.8,292.3,299
XS GIS Cut Line= 3
     2100491.872      382677.587     2100441.177      382804.324
     2100390.482      382931.061
#Sta/Elev= 24
       0 3251.12     9.8 3248.66    19.5 3246.37    29.2 3244.23      39 3242.24
    48.8 3240.48    58.5 3238.92    68.2 3237.52      78 3236.27    97.5 3234.02
   117.8 3231.48   126.8 3230.84   132.8 3231.23   136.5 3231.47   146.2 3233.73
     156 3236.26   165.8 3238.27   175.5 3240.15   204.8 3245.66   224.2 3249.61
     234 3251.78   253.5 3256.28   263.2 3258.74     273  3261.7
#Mann= 3 , 0 , 0
       0      .1       0   117.8    .045       0   132.8      .1       0
Bank Sta=117.8,132.8
XS Rating Curve= 0 ,0
Exp/Cntr=0.3,0.1

Type RM Length L Ch R = 1 ,5080.6  ,302,299.5,296.9
XS GIS Cut Line= 3
     2100250.171      382591.502      2100172.12      382703.488
     2100093.565      382815.117
#Sta/Elev= 18
       0 3249.22     9.8 3246.42    19.5 3243.75    29.2 3241.18    48.8 3236.22
      78 3229.15    87.8 3226.93    97.5 3224.97   107.2 3223.43     117  3222.2
   117.5 3222.19   126.8 3221.85   132.5 3222.32   136.5 3222.64   146.2 3224.74
     156 3227.12   175.5 3230.88     273 3248.38
#Mann= 3 , 0 , 0
       0      .1       0   117.5    .045       0   132.5      .1       0
Bank Sta=117.5,132.5
XS Rating Curve= 0 ,0
Exp/Cntr=0.3,0.1

Type RM Length L Ch R = 1 ,4781.1  ,336.7,324.8,312.8
XS GIS Cut Line= 2
     2100009.404      382388.611     2099878.324      382629.771
#Sta/Elev= 19
       0    3274    19.6 3265.51    29.4 3261.16      49 3252.19    58.8 3247.54
    68.6 3243.01    78.4 3238.66      98 3230.39   107.8 3225.95   117.6 3221.04
   127.4 3216.74   130.1 3216.32   137.2 3215.21   145.1 3215.79     147 3215.93
   166.6 3219.18   196.1  3223.5   215.7 3226.47   274.5 3235.87
#Mann= 3 , 0 , 0
       0      .1       0   130.1    .045       0   145.1      .1       0
Bank Sta=130.1,145.1
XS Rating Curve= 0 ,0
Exp/Cntr=0.3,0.1

Type RM Length L Ch R = 1 ,4456.4  ,245.1,268.4,291.6
XS GIS Cut Line= 2
     2099669.545      382446.593      2099676.05      382720.655
#Sta/Elev= 26
       0 3213.88     9.8 3212.72    19.6 3211.66    29.4 3210.74    39.2 3209.96
      49  3209.3    58.7  3208.8    68.5 3208.43   117.5 3207.29   127.3 3206.95
   137.1 3206.31   144.4 3205.67   146.9 3205.46   156.6 3205.26   159.4    3206
   166.4 3207.89   176.2 3214.37     186 3221.52   195.8  3227.4   215.4 3238.39
   225.2 3243.34     235 3246.71   244.8 3248.61   254.6  3249.8   264.4 3250.72
   274.1 3251.37
#Mann= 3 , 0 , 0
       0      .1       0   144.4    .045       0   159.4      .1       0
Bank Sta=144.4,159.4
XS Rating Curve= 0 ,0
Exp/Cntr=0.3,0.1

Type RM Length L Ch R = 1 ,4188    ,308.9,299.8,290.7
XS GIS Cut Line= 2
     2099551.596      382428.443     2099318.009      382579.255
#Sta/Elev= 22
       0  3207.5    19.9 3205.22    39.7 3203.06    59.6 3201.21    89.4 3198.73
   109.2 3196.97   128.2 3194.97   129.1 3194.88     139 3194.62   143.2 3195.46
     149 3196.62   158.9 3201.06   168.8 3206.02   178.7  3210.7   188.7 3215.18
   208.5 3224.38   228.4 3233.21   238.3 3237.37   248.2 3241.32   258.2 3244.95
   268.1 3247.52     278  3248.9
#Mann= 3 , 0 , 0
       0      .1       0   128.2    .045       0   143.2      .1       0
Bank Sta=128.2,143.2
XS Rating Curve= 0 ,0
Exp/Cntr=0.3,0.1

Type RM Length L Ch R = 1 ,3888.2  ,307.8,297.4,287
XS GIS Cut Line= 2
     2099389.065      382131.875     2099236.402      382360.252
#Sta/Elev= 21
       0 3231.84     9.8 3227.88    29.4 3220.23    39.2 3216.91      49 3214.02
    68.7  3208.8    78.5  3206.1    88.3 3202.89    98.1 3199.16   107.9 3194.95
   117.7 3190.54   125.5 3187.59   127.5 3186.81   137.4 3185.42   140.5 3185.84
   147.2 3186.74     157 3189.22   166.8 3191.83   176.6 3194.15   235.5 3207.85
   274.7 3216.58
#Mann= 3 , 0 , 0
       0      .1       0   125.5    .045       0   140.5      .1       0
Bank Sta=125.5,140.5
XS Rating Curve= 0 ,0
Exp/Cntr=0.3,0.1

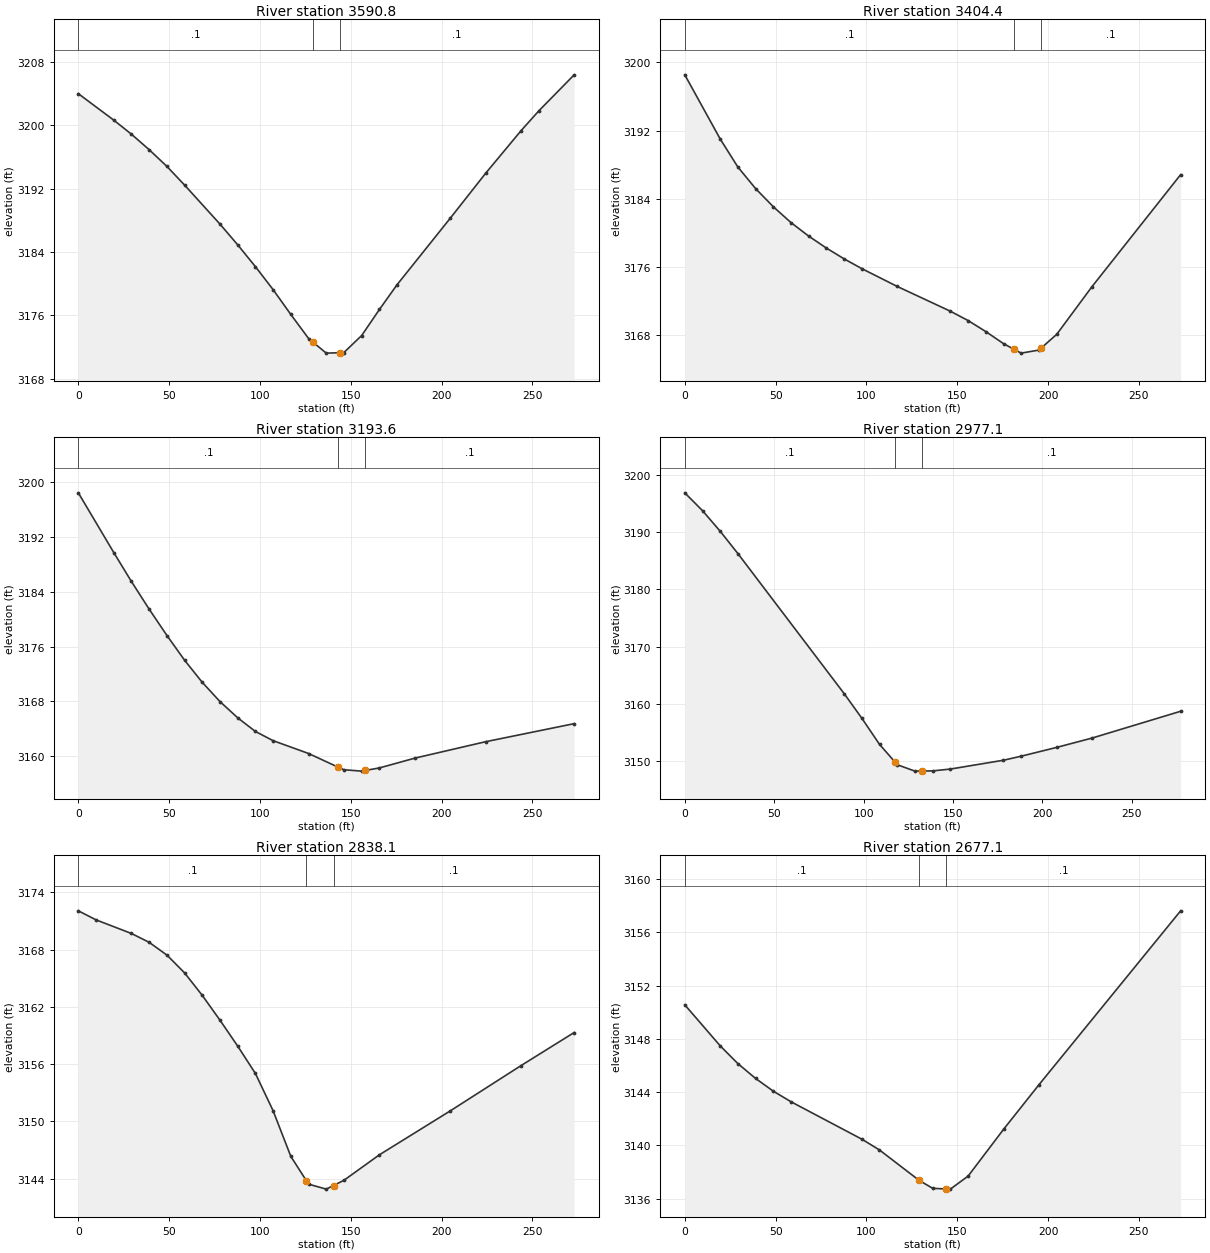
Type RM Length L Ch R = 1 ,3590.8  ,172.5,186.4,199.1
XS GIS Cut Line= 3
      2099050.16      382016.536      2099032.58        382151.9
     2099015.001      382287.263
#Sta/Elev= 24
       0    3204    19.5 3200.66    29.2 3198.89      39 3196.93    48.8 3194.81
    58.5 3192.46      78 3187.53    87.8  3184.9    97.5 3182.16   107.2 3179.27
     117 3176.12   126.8 3173.08     129 3172.66   136.5 3171.24     144 3171.29
   146.2 3171.31     156 3173.46   165.8 3176.76   175.5 3179.88   204.8 3188.28
   224.2 3193.93   243.8 3199.34   253.5 3201.82     273 3206.38
#Mann= 3 , 0 , 0
       0      .1       0     129    .045       0     144      .1       0
Bank Sta=129,144
XS Rating Curve= 0 ,0
Exp/Cntr=0.3,0.1

Type RM Length L Ch R = 1 ,3404.4  ,205.7,210.8,218.2
XS GIS Cut Line= 3
      2098968.21      381970.933     2098882.384      382077.076
     2098796.559      382183.218
#Sta/Elev= 22
       0 3198.55    19.5 3191.02    29.2 3187.74      39  3185.2    48.8 3183.06
    58.5 3181.21    68.2 3179.63      78 3178.22    87.8 3176.95    97.5 3175.81
     117 3173.72   146.2 3170.82     156 3169.72   165.8 3168.42   175.5 3167.01
   181.1 3166.37   185.2  3165.9     195 3166.26   196.1 3166.47   204.8 3168.11
   224.2  3173.7     273 3186.84
#Mann= 3 , 0 , 0
       0      .1       0   181.1    .045       0   196.1      .1       0
Bank Sta=181.1,196.1
XS Rating Curve= 0 ,0
Exp/Cntr=0.3,0.1

Type RM Length L Ch R = 1 ,3193.6  ,236,216.5,197
XS GIS Cut Line= 3
     2098871.334      381859.587     2098756.657      381933.623
     2098641.979      382007.659
#Sta/Elev= 20
       0 3198.45    19.5 3189.74    29.2 3185.52      39 3181.47    48.8 3177.62
    58.5 3174.02    68.2  3170.8      78 3167.98    87.8  3165.6    97.5 3163.62
   107.2 3162.28   126.8  3160.4   143.1  3158.4   146.2 3158.03     156 3157.83
   158.1 3157.93   165.8  3158.3   185.2 3159.72   224.2 3162.12     273 3164.76
#Mann= 3 , 0 , 0
       0      .1       0   143.1    .045       0   158.1      .1       0
Bank Sta=143.1,158.1
XS Rating Curve= 0 ,0
Exp/Cntr=0.3,0.1

Type RM Length L Ch R = 1 ,2977.1  ,148.6,139,129.4
XS GIS Cut Line= 2
     2098616.182      381677.244     2098576.111      381951.601
#Sta/Elev= 18
       0 3196.82     9.9 3193.71    19.8 3190.12    29.7 3186.22    89.1 3161.81
      99 3157.51   108.9 3152.95   117.7 3149.81   118.8  3149.4   128.7 3148.28
   132.7  3148.3   138.6 3148.32   148.5 3148.64   178.2 3150.18   188.2 3150.89
     208 3152.42   227.8 3154.05   277.3 3158.72
#Mann= 3 , 0 , 0
       0      .1       0   117.7    .045       0   132.7      .1       0
Bank Sta=117.7,132.7
XS Rating Curve= 0 ,0
Exp/Cntr=0.3,0.1

Type RM Length L Ch R = 1 ,2838.1  ,154.4,161,167.6
XS GIS Cut Line= 3
     2098428.969      381710.025     2098465.276      381841.608
     2098501.583      381973.191
#Sta/Elev= 21
       0 3172.06     9.8 3171.11    29.2 3169.69      39 3168.76    48.8 3167.42
    58.5 3165.56    68.2 3163.21      78  3160.6    87.8 3157.87    97.5 3155.02
   107.2 3151.13     117 3146.33   125.5  3143.8   126.8 3143.42   136.5  3142.9
   140.5 3143.28   146.2 3143.82   165.8  3146.5   204.8  3151.1   243.8 3155.85
     273 3159.31
#Mann= 3 , 0 , 0
       0      .1       0   125.5    .045       0   140.5      .1       0
Bank Sta=125.5,140.5
XS Rating Curve= 0 ,0
Exp/Cntr=0.3,0.1

Type RM Length L Ch R = 1 ,2677.1  ,287.6,300,312.4
XS GIS Cut Line= 3
     2098313.727      381742.737     2098311.857      381879.225
     2098309.987      382015.712
#Sta/Elev= 16
       0 3150.56    19.5 3147.48    29.2 3146.15      39 3145.03    48.8 3144.07
    58.5 3143.28    97.5 3140.47   107.2 3139.66     129 3137.38   136.5 3136.78
     144 3136.73   146.2 3136.72     156  3137.7   175.5 3141.21     195 3144.56
     273 3157.62
#Mann= 3 , 0 , 0
       0      .1       0     129    .045       0     144      .1       0
Bank Sta=129,144
XS Rating Curve= 0 ,0
Exp/Cntr=0.3,0.1

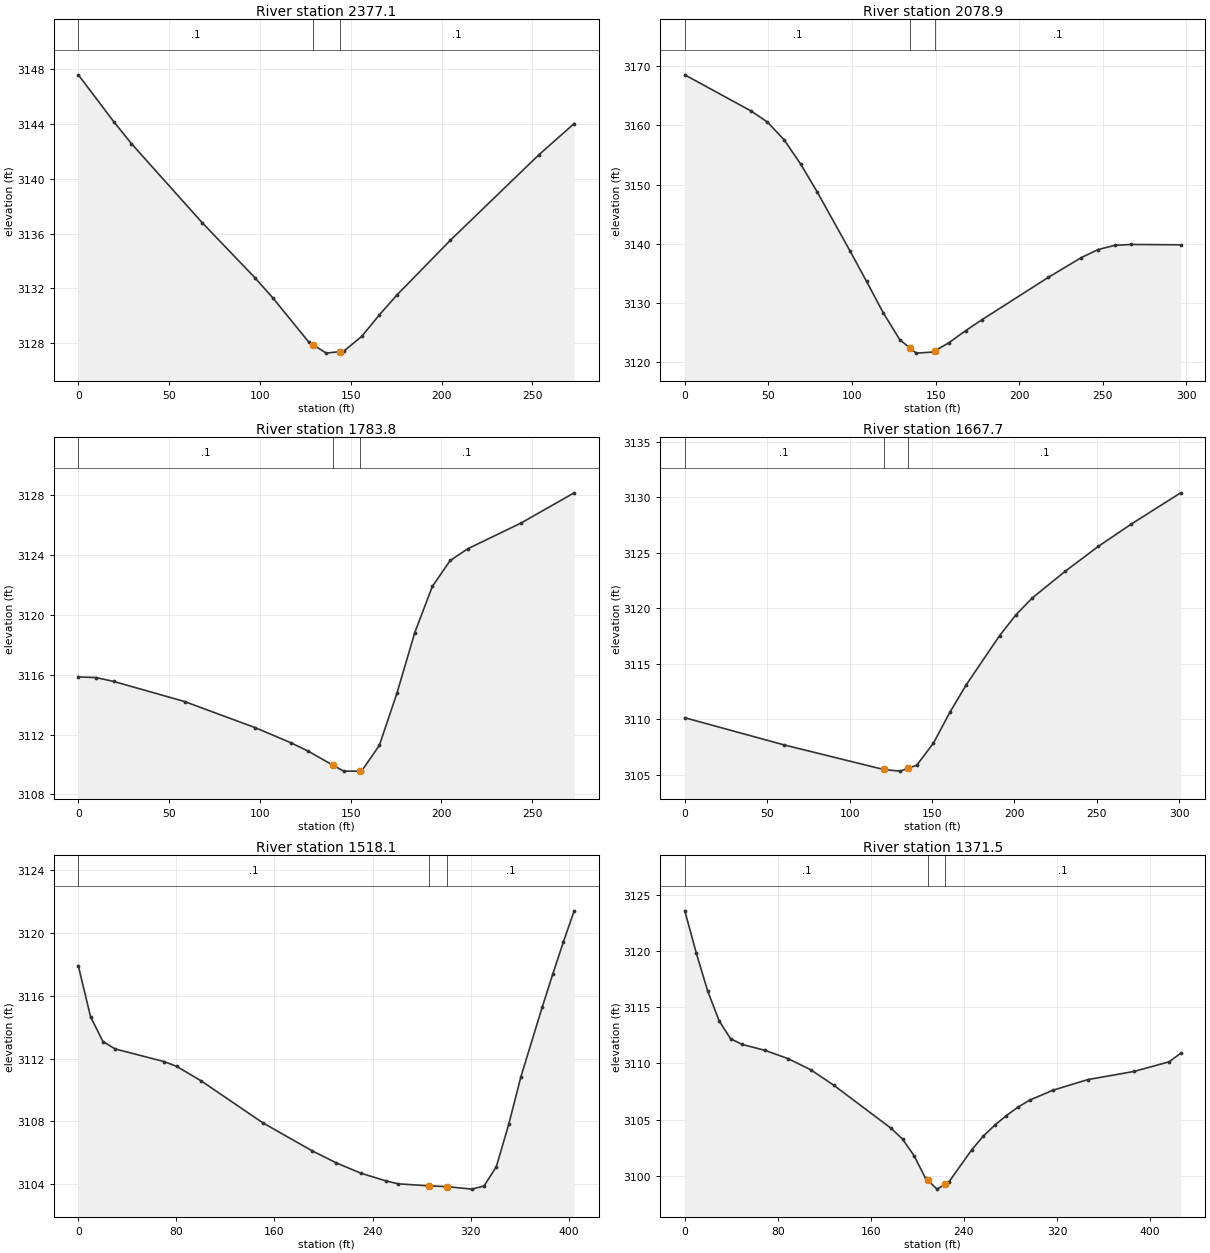
Type RM Length L Ch R = 1 ,2377.1  ,312.3,298.2,284.2
XS GIS Cut Line= 3
     2098106.899      381663.765     2098034.288       381779.35
     2097961.677      381894.935
#Sta/Elev= 17
       0  3147.6    19.5 3144.18    29.2 3142.58    68.2  3136.8    97.5 3132.74
   107.2 3131.29   126.8 3128.09     129  3127.9   136.5 3127.27     144 3127.38
   146.2 3127.42     156 3128.49   165.8 3130.07   175.5 3131.53   204.8 3135.51
   253.5 3141.75     273 3144.04
#Mann= 3 , 0 , 0
       0      .1       0     129    .045       0     144      .1       0
Bank Sta=129,144
XS Rating Curve= 0 ,0
Exp/Cntr=0.3,0.1

Type RM Length L Ch R = 1 ,2078.9  ,301.3,295.1,291.7
XS GIS Cut Line= 2
     2097776.994      381478.266     2097793.872      381774.268
#Sta/Elev= 23
       0 3168.57    39.5 3162.47    49.4 3160.58    59.3  3157.6    69.2  3153.5
    79.1 3148.78    98.8 3138.76   108.7 3133.59   118.6 3128.32   128.5 3123.74
   134.6 3122.32   138.4 3121.45   148.2 3121.63   149.6 3121.85   158.1 3123.24
     168 3125.27   177.9 3127.14   217.4 3134.28   237.2 3137.64   247.1 3138.98
     257 3139.69   266.8 3139.85   296.5 3139.79
#Mann= 3 , 0 , 0
       0      .1       0   134.6    .045       0   149.6      .1       0
Bank Sta=134.6,149.6
XS Rating Curve= 0 ,0
Exp/Cntr=0.3,0.1

Type RM Length L Ch R = 1 ,1783.8  ,120.9,116,110.8
XS GIS Cut Line= 3
     2097492.605      381629.113     2097539.337      381757.341
     2097581.143      381887.411
#Sta/Elev= 19
       0 3115.85     9.8 3115.81    19.5 3115.55    58.5 3114.21    97.5 3112.46
     117 3111.46   126.7 3110.89     140 3109.97   146.2 3109.56     155 3109.56
     156 3109.56   165.8 3111.28   175.5 3114.77   185.3 3118.81     195  3121.9
   204.8 3123.63   214.6 3124.42   243.8 3126.13   273.1 3128.15
#Mann= 3 , 0 , 0
       0      .1       0     140    .045       0     155      .1       0
Bank Sta=140,155
XS Rating Curve= 0 ,0
Exp/Cntr=0.3,0.1

Type RM Length L Ch R = 1 ,1667.7  ,142.6,149.6,168.8
XS GIS Cut Line= 3
     2097374.305      381705.351     2097466.993       381860.78
     2097547.981      381949.177
#Sta/Elev= 17
       0 3110.15    60.3  3107.7   120.6 3105.49   120.6 3105.48   130.7 3105.34
   135.6  3105.6   140.8 3105.88   150.8 3107.84   160.9 3110.65   170.9 3113.14
     191 3117.54     201 3119.43   210.9 3120.94   230.9 3123.35   250.9 3125.58
   270.9 3127.59   300.9 3130.41
#Mann= 3 , 0 , 0
       0      .1       0   120.6    .045       0   135.6      .1       0
Bank Sta=120.6,135.6
XS Rating Curve= 0 ,0
Exp/Cntr=0.3,0.1

Type RM Length L Ch R = 1 ,1518.1  ,138.6,146.6,165.4
XS GIS Cut Line= 3
     2097393.522      381598.472     2097293.476      381945.443
      2097301.99      381988.016
#Sta/Elev= 24
       0 3117.91      10 3114.66    20.1 3113.08    30.1 3112.61    70.2  3111.8
    80.2  3111.5   100.3 3110.57   150.5  3107.9   190.6 3106.12   210.6 3105.34
   230.7 3104.68   250.8  3104.2   260.8 3104.01   285.9 3103.88   300.9 3103.83
     321 3103.67     331 3103.87     341  3105.1   351.1  3107.8   361.1 3110.85
   378.5 3115.29   387.2 3117.42   395.8 3119.46   404.5 3121.42
#Mann= 3 , 0 , 0
       0      .1       0   285.9    .045       0   300.9      .1       0
Bank Sta=285.9,300.9
XS Rating Curve= 0 ,0
Exp/Cntr=0.3,0.1

Type RM Length L Ch R = 1 ,1371.5  ,160.6,147.8,135.1
XS GIS Cut Line= 3
     2097371.172      381579.314     2097234.937      381784.729
      2097215.78      381963.537
#Sta/Elev= 29
       0 3123.57     9.9 3119.81    19.7 3116.43    29.6 3113.77    39.4 3112.19
    49.3 3111.69      69 3111.16    88.7 3110.43   108.4 3109.43   128.2 3108.05
   177.5 3104.22   187.3 3103.26   197.2 3101.78     207 3099.78   208.9  3099.6
   216.9 3098.82   223.9 3099.24   226.8 3099.42   246.5 3102.29   256.5 3103.52
   266.5 3104.51   276.5 3105.36   286.4 3106.11   296.4 3106.73   316.4 3107.61
   346.4 3108.56   386.4 3109.29   416.3 3110.14   426.3  3110.9
#Mann= 3 , 0 , 0
       0      .1       0   208.9    .045       0   223.9      .1       0
Bank Sta=208.9,223.9
XS Rating Curve= 0 ,0
Exp/Cntr=0.3,0.1