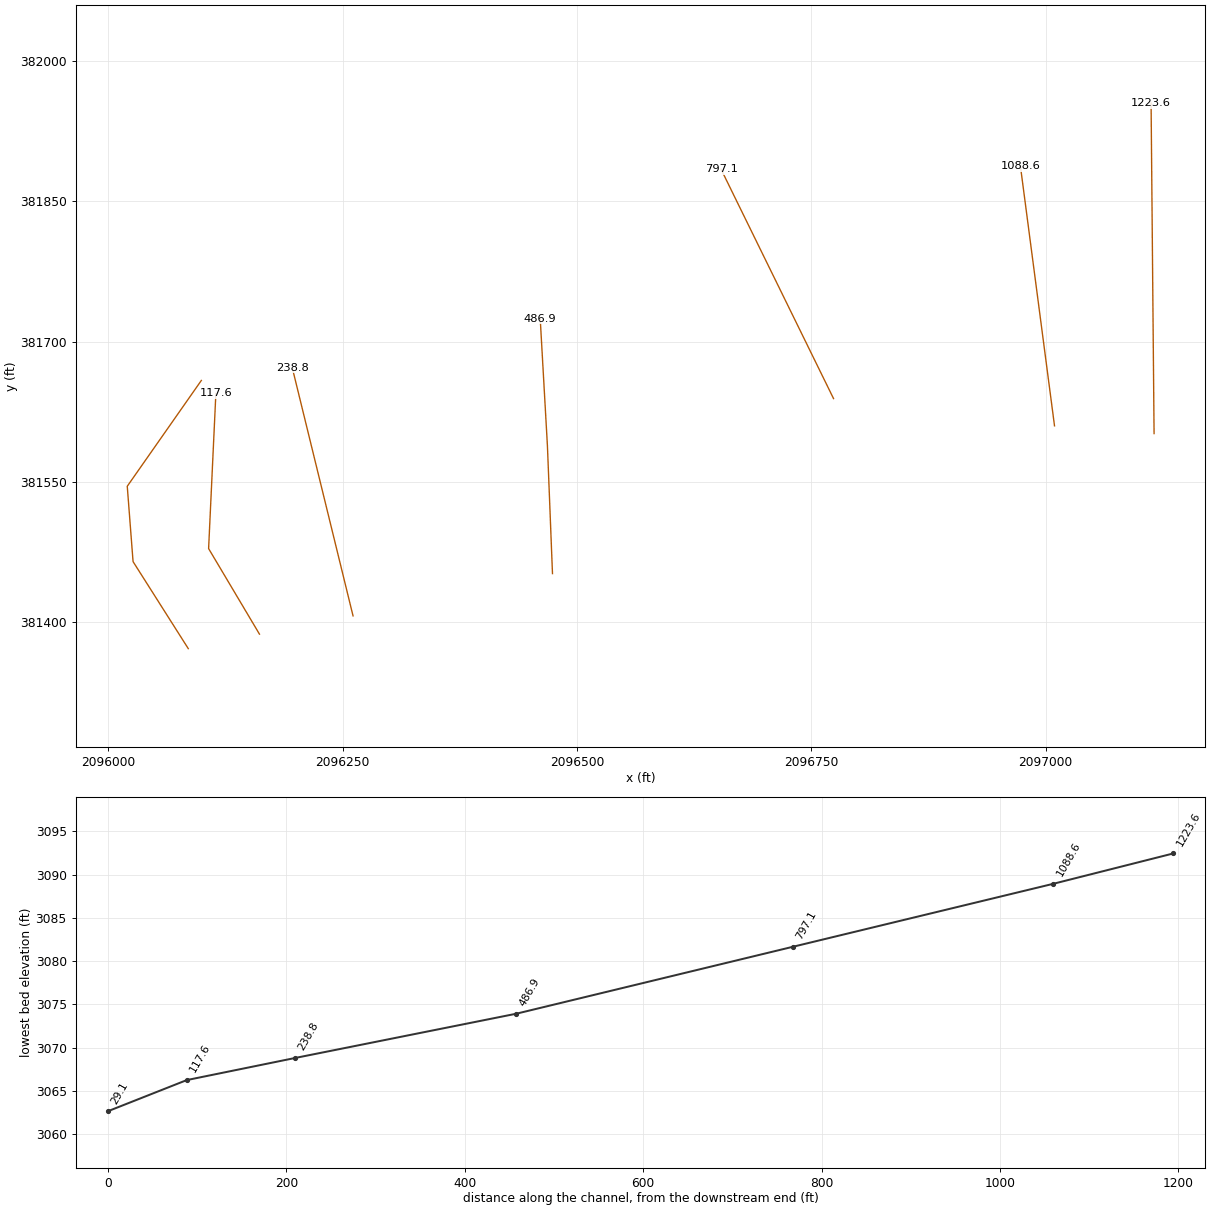
HEC-RAS study OldFieldBr.prj: OldFieldBr

--- OldFieldBr.g01 (geometry) --- (continued)

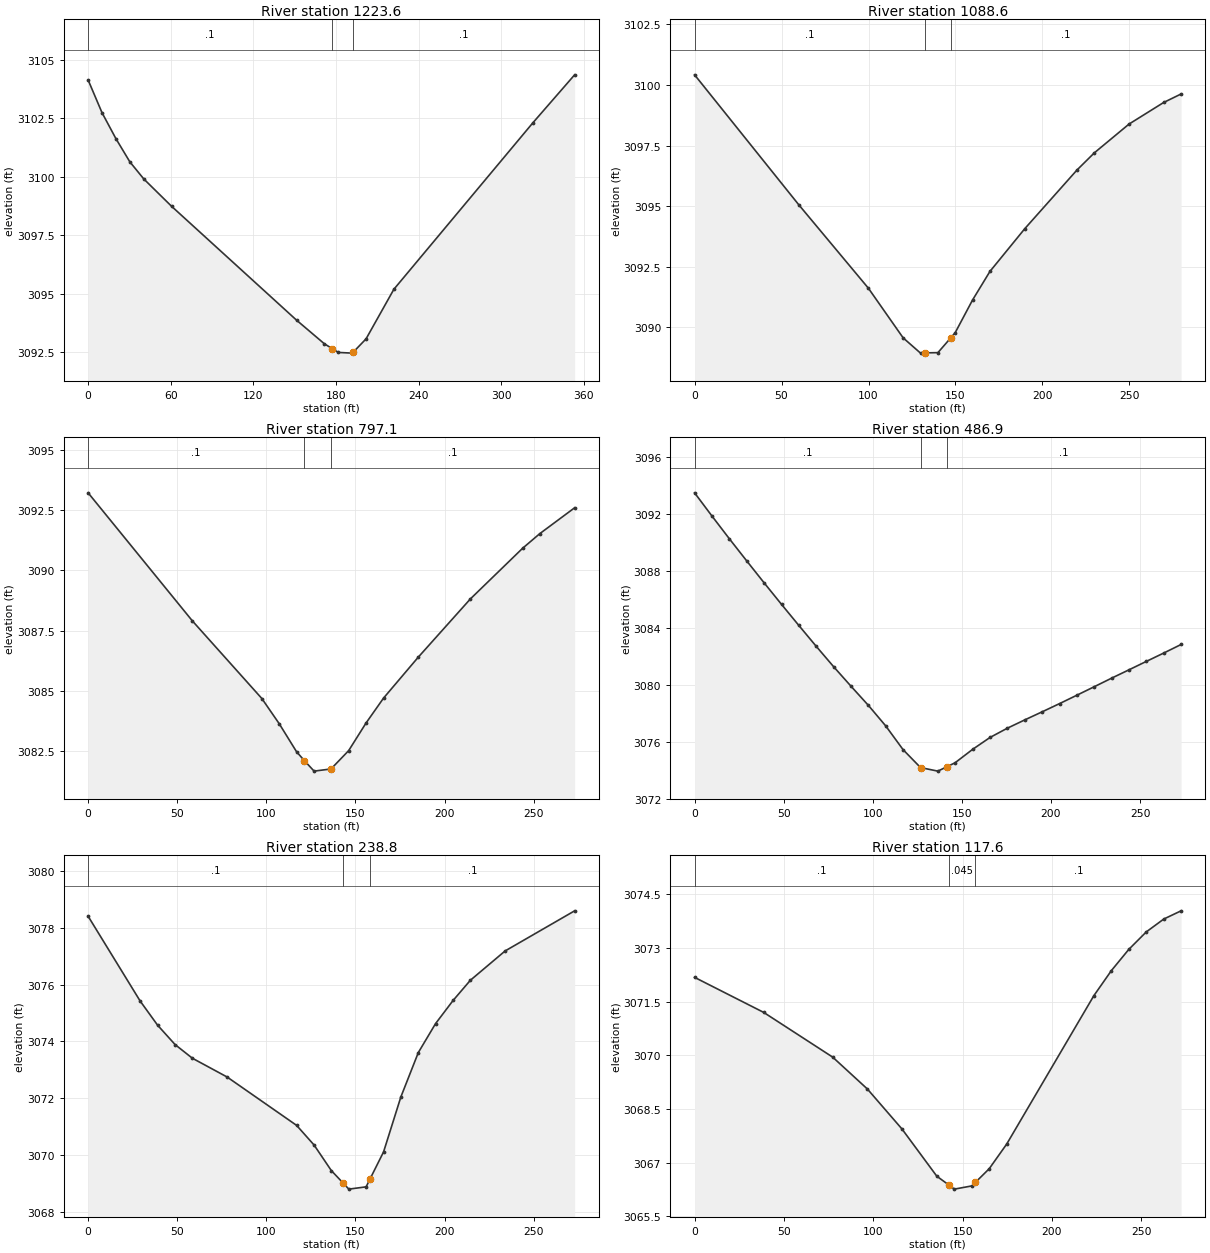
Type RM Length L Ch R = 1 ,1223.6  ,132.2,135,137.8
XS GIS Cut Line= 2
     2097115.733      381601.665      2097112.54      381955.022
#Sta/Elev= 16
       0 3104.14    10.1 3102.74    20.2 3101.63    30.3 3100.64    40.4 3099.91
    60.6 3098.74   151.4 3093.87   171.6 3092.86   177.4 3092.65   181.7 3092.49
   191.8 3092.46   192.4 3092.49   201.9 3093.07   222.1 3095.19   323.1 3102.31
   353.4 3104.36
#Mann= 3 , 0 , 0
       0      .1       0   177.4    .045       0   192.4      .1       0
Bank Sta=177.4,192.4
XS Rating Curve= 0 ,0
Exp/Cntr=0.3,0.1

Type RM Length L Ch R = 1 ,1088.6  ,284.2,291.5,298.9
XS GIS Cut Line= 2
     2097009.508      381609.957     2096973.173      381887.309
#Sta/Elev= 17
       0 3100.42    59.9 3095.06    99.9 3091.62   119.9 3089.57   129.9 3088.94
   132.4 3088.95   139.9 3088.96   147.4 3089.58   149.8 3089.78   159.8 3091.13
   169.8 3092.31   189.8 3094.07   219.8 3096.49   229.8  3097.2   249.8 3098.39
   269.7 3099.28   279.7 3099.63
#Mann= 3 , 0 , 0
       0      .1       0   132.4    .045       0   147.4      .1       0
Bank Sta=132.4,147.4
XS Rating Curve= 0 ,0
Exp/Cntr=0.3,0.1

Type RM Length L Ch R = 1 ,797.1   ,319.6,310.2,301.1
XS GIS Cut Line= 3
     2096773.755      381639.071     2096713.757      381761.677
     2096653.758      381884.284
#Sta/Elev= 16
       0 3093.21    58.5  3087.9    97.5 3084.68   107.2 3083.64     117 3082.47
   121.3 3082.11   126.8 3081.67   136.3 3081.76   146.2 3082.52     156 3083.67
   165.8  3084.7   185.2 3086.39   214.5 3088.81   243.8 3090.91   253.5 3091.52
     273 3092.59
#Mann= 3 , 0 , 0
       0      .1       0   121.3    .045       0   136.3      .1       0
Bank Sta=121.3,136.3
XS Rating Curve= 0 ,0
Exp/Cntr=0.3,0.1

Type RM Length L Ch R = 1 ,486.9   ,243.6,248.1,252.3
XS GIS Cut Line= 3
     2096473.887      381451.977     2096468.494      381588.366
     2096460.783      381724.672
#Sta/Elev= 30
       0 3093.51     9.8 3091.87    19.5 3090.28    29.2 3088.73      39 3087.18
    48.8 3085.66    58.5 3084.18    68.2 3082.72      78 3081.28    87.8  3079.9
    97.5 3078.56   107.2 3077.12     117 3075.44   126.8 3074.18   136.5 3073.93
   141.8 3074.25   146.2 3074.52     156 3075.46   165.8  3076.3   175.5 3076.95
   185.2 3077.53     195  3078.1   204.8 3078.68   214.5 3079.27   224.3 3079.87
     234 3080.47   243.8 3081.06   253.5 3081.65   263.3 3082.24     273 3082.84
#Mann= 3 , 0 , 0
       0      .1       0   126.8    .045       0   141.8      .1       0
Bank Sta=126.8,141.8
XS Rating Curve= 0 ,0
Exp/Cntr=0.3,0.1

Type RM Length L Ch R = 1 ,238.8   ,127.7,121.2,114.7
XS GIS Cut Line= 2
     2096261.094      381406.724     2096196.279      381671.951
#Sta/Elev= 21
       0  3078.4    29.2 3075.42      39 3074.57    48.8 3073.89    58.5 3073.41
      78 3072.75     117 3071.05   126.8 3070.36   136.5 3069.46   143.3 3069.01
   146.3 3068.81     156 3068.89   158.3 3069.18   165.8 3070.12   175.5 3072.05
   185.3 3073.61     195 3074.63   204.8 3075.44   214.5 3076.15     234 3077.18
     273 3078.59
#Mann= 3 , 0 , 0
       0      .1       0   143.3    .045       0   158.3      .1       0
Bank Sta=143.3,158.3
XS Rating Curve= 0 ,0
Exp/Cntr=0.3,0.1

Type RM Length L Ch R = 1 ,117.6   ,85.9,88.4,91
XS GIS Cut Line= 3
     2096161.238       381387.26     2096106.992      381478.703
     2096114.742      381644.541
#Sta/Elev= 18
       0 3072.18    38.7  3071.2    77.3 3069.95    96.7 3069.06   116.1 3067.94
   135.6 3066.62   142.2 3066.38   145.4 3066.26   155.2 3066.35   157.2 3066.45
   164.9 3066.83   174.7 3067.52   223.5 3071.67   233.3 3072.37     243 3072.96
   252.8 3073.45   262.6 3073.81   272.3 3074.04
#Mann= 3 , 0 , 0
       0      .1       0   142.2    .045       0   157.2      .1       0
Bank Sta=142.2,157.2
XS Rating Curve= 0 ,0
Exp/Cntr=0.3,0.1

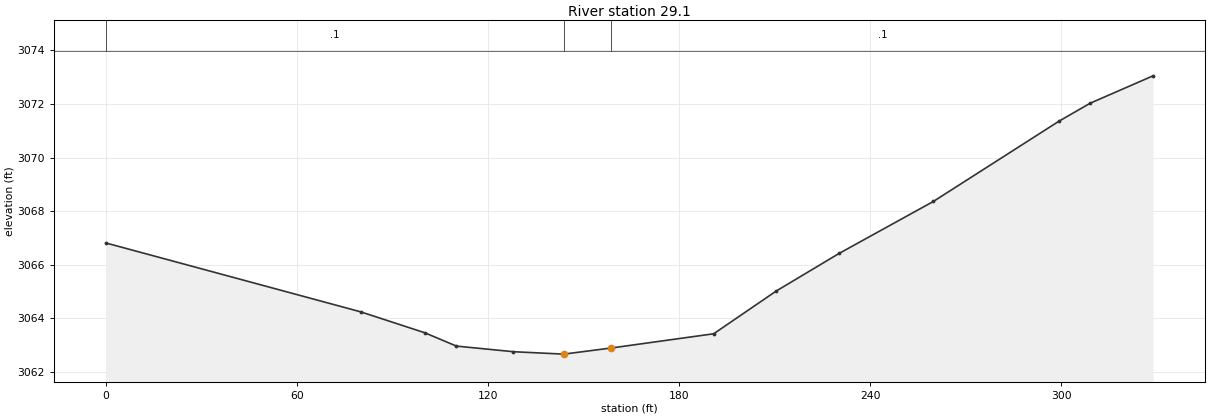
Type RM Length L Ch R = 1 ,29.1    ,21,29.1,37.3
XS GIS Cut Line= 4
     2096085.294      381371.761     2096026.398      381464.754
     2096020.199      381545.348     2096099.243       381658.49
#Sta/Elev= 14
       0 3066.81      80 3064.24   100.1 3063.46   110.1 3062.96     128 3062.75
   143.8 3062.66   158.8 3062.89   190.9 3063.42   210.6 3065.02   230.3 3066.42
   259.9 3068.36   299.4 3071.36   309.2 3072.03   328.9 3073.05
#Mann= 3 , 0 , 0
       0      .1       0   143.8    .045       0   158.8      .1       0
Bank Sta=143.8,158.8
XS Rating Curve= 0 ,0
Exp/Cntr=0.3,0.1

Chan Stop Cuts=-1
Use User Specified Reach Order=0